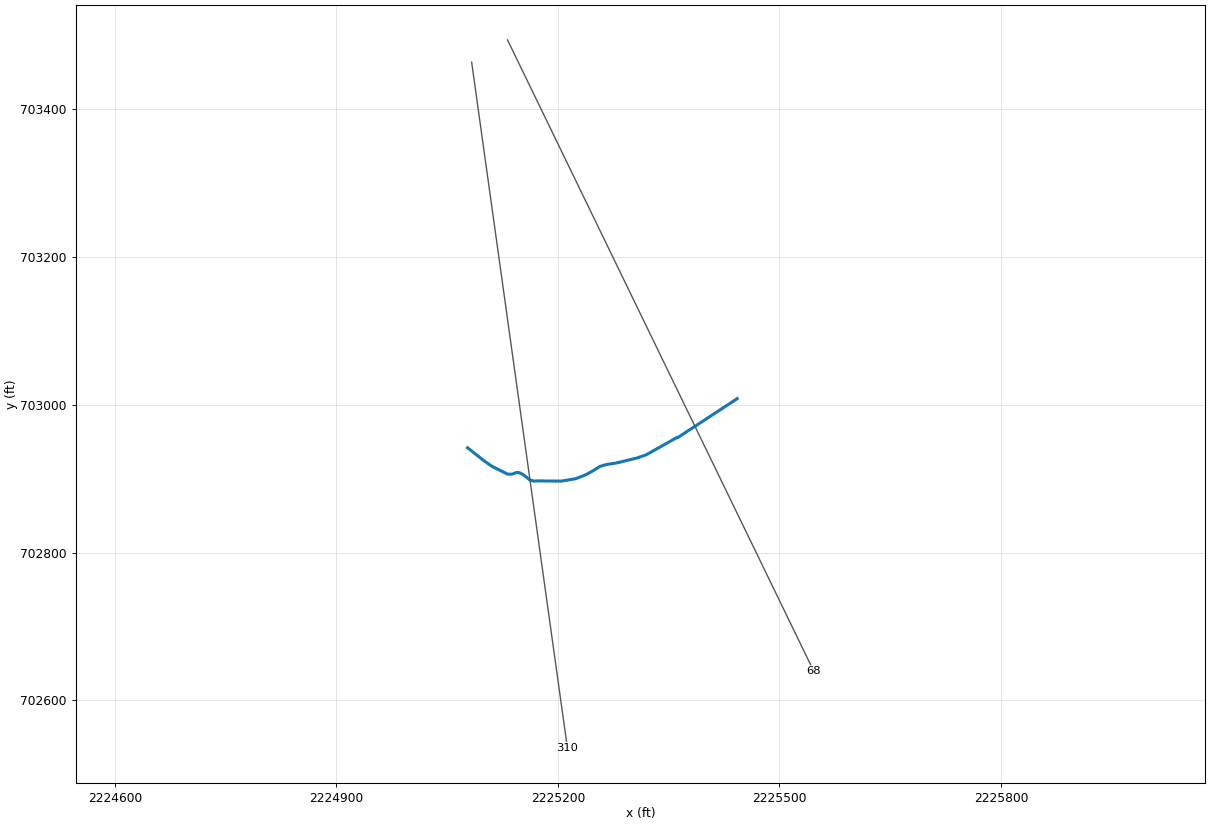
--- GUMRN.prj (project) ---

Proj Title=GUMRN
Current Plan=p01
Default Exp/Contr=0,0
English Units
Geom File=g01
Flow File=f01
Plan File=p01
BEGIN DESCRIPTION:
END DESCRIPTION:
DSS Export Rating Curves= 0
DSS Export Rating Curve Sorted= 0
DSS Export Volume Flow Curves= 0
DXF OffsetX= 0
DXF OffsetY= 0
DXF ScaleX= 0
DXF ScaleY= 0

--- GUMRN.p01 (plan) ---

Plan Title=Floodplain
Program Version=6.20
Short Identifier=Floodplain
Geom File=g01
Flow File=f01
Subcritical Flow
K Sum by GR= 0
Std Step Tol= 0.01
Critical Tol= 0.01
Num of Std Step Trials= 20
Max Error Tol= 0.3
Flow Tol Ratio= 0.001
Split Flow NTrial= 30
Split Flow Tol= 0.02
Split Flow Ratio= 0.02
Log Output Level= 0
Friction Slope Method= 1
Unsteady Friction Slope Method= 2
Unsteady Bridges Friction Slope Method= 1
Parabolic Critical Depth
Global Vel Dist= 0 , 0 , 0
Global Log Level= 0
CheckData=True
Encroach Param=-1 ,0,0, 0
Mapping Interval=1HOUR
Computation Time Step Use Courant=        0
Computation Time Step Use Time Series=    0
Computation Time Step Count To Double=0
Computation Time Step Max Doubling=0
Computation Time Step Max Halving=0
Computation Time Step Residence Courant=0
Run HTab= 0
Run UNet= 0
Run Sediment= 0
Run PostProcess= 0
Run WQNet= 0
Run RASMapper=-1
UNET Theta= 0
UNET Theta Warmup= 0
UNET ZTol= 0
UNET ZSATol= 0
UNET MxIter= 0
UNET Max Iter WO Improvement= 0
UNET MaxInSteps= 0
UNET DtIC= 0
UNET DtMin= 0
UNET MaxCRTS= 0
UNET WFStab= 0
UNET SFStab= 0
UNET WFX= 1
UNET SFX= 1
UNET Gravity=32.174
UNET 1D Methodology=Finite Difference
UNET DSS MLevel= 1
UNET Pardiso=0
UNET DZMax Abort= 0
UNET Use Existing IB Tables= 0
UNET Froude Reduction=False
UNET Froude Limit= 0
UNET Froude Power= 0
UNET D1 Cores= 0
UNET WindReference=Eulerian
UNET WindDragFormulation=Hsu (1988)
UNET D2 Coriolis=0
UNET D2 Cores= 0
UNET D2 Theta= 1
UNET D2 Theta Warmup= 1
UNET D2 Z Tol= 0.01
UNET D2 Volume Tol= 0.01
UNET D2 Max Iterations= 20
UNET D2 Equation= 0
UNET D2 RampUpFraction=0.1
UNET D2 TimeSlices= 1
UNET D2 Turbulence Formulation=Non-Conservative (original)
UNET D2 Eddy Viscosity=0.3
UNET D2 Transverse Eddy Viscosity=0.1
UNET D2 Smagorinsky Mixing=0
UNET D2 BCVolumeCheck=0
UNET D2 Cores=0
UNET D2 SolverType=PARDISO (Direct)
UNET D2 Minimum Iterations= 2147483647
UNET D2 Maximum Iterations= 2147483647
UNET D2 Restart Number= 10
UNET D2 Relaxation Coeff=1.3
UNET D2 SOR Precondition Iterations= 10
UNET D2 ILUT Maximum Fill= 8
UNET D2 ILUT Tolerance=1E-08
UNET D1D2 MaxIter= 0
UNET D1D2 ZTol=0.01
UNET D1D2 QTol=0.1
UNET D1D2 MinQTol=1
Write IC File= 0
Write IC File at Fixed DateTime=0
Write IC File at Sim End=0
Echo Input=False
Echo Parameters=False
Echo Output=False
Write Detailed= 0
HDF Write Warmup=0
HDF Write Time Slices=0
HDF Flush=0
HDF Compression= 1
HDF Chunk Size= 1
HDF Spatial Parts= 1
HDF Use Max Rows=0
HDF Fixed Rows= 1
Calibration Method= 0
Calibration Iterations= 20
Calibration Max Change=0.05
Calibration Tolerance=0.2
Calibration Maximum=1.5
Calibration Minimum=0.5
Calibration Optimization Method= 1
WQ AD Non Conservative
WQ ULTIMATE=-1
WQ Max Comp Step=1HOUR
WQ Output Interval=15MIN
WQ Output Selected Increments= 0
WQ Output face flow=0
WQ Output face velocity=0
WQ Output face area=0
WQ Output face dispersion=0
WQ Output cell volume=0
WQ Output cell surface area=0
WQ Output cell continuity=0
WQ Output cumulative cell continuity=0
WQ Output face conc=0
WQ Output face dconc_dx=0
WQ Output face courant=0
WQ Output face peclet=0
WQ Output face adv mass=0
WQ Output face disp mass=0
WQ Output cell mass=0
WQ Output cell source sink temp=0
WQ Output nsm pathways=0
WQ Output nsm derived pathways=0
WQ Create Restart=0
WQ Fixed Restart=0
WQ System Summary=0
WQ Write To DSS=0
Sorting and Armoring Iterations= 10
XS Update Threshold= 0.02
Bed Roughness Predictor= 0
Hydraulics Update Threshold= 0.02
Energy Slope Method= 1
Volume Change Method= 1
Sediment Retention Method= 0
Sediment TS Multiplier= 1
Warm Up Method= 0
XS Weighting Method= 0
Number of US Weighted Cross Sections= 1
Number of DS Weighted Cross Sections= 1
Upstream XS Weight=0
Main XS Weight=1
Downstream XS Weight=0
Number of DS XS's Weighted with US Boundary= 1
Upstream Boundary Weight= 1
Weight of XSs Associated with US Boundary= 0
Number of US XS's Weighted with DS Boundary= 1
Downstream Boundary Weight= 0.5
Weight of XSs Associated with DS Boundary= 0.5
Percentile Method= 0
Sediment Output Level= 3
Mass or Volume Output= 0
Output Increment Type= 1
Profile and TS Output Increment= 1
Transport Output Increment 1
XS Output Flag= 0
XS Output Increment= 10
Read HDF5 Sediment Hotstart= 0
Sediment Hotstart Type= 0
Write Gradation File= 0
Read Gradation Hotstart= 0
Write HDF5 File= 1
Write Binary Output= 1
Write DSS Sediment File= 0
DSS Sediment Output Type= 1
SV Curve= 0
Specific Gage Flag= 0
Subcell Erosion Methods= 0
Subcell Deposition Methods= 0
Advection Scheme= 1
Matrix Solver= 0
Implicit Weighting Factor= 1
Maximum Outer Loop Convergence Iterations= 5
Convergence Maximum Absolute= 0.001
Convergence RMSE= 0.0001
Grain Fractions Max Abs Error= 0.001
Max Subgrid Regions= 1
Max Subgrid Length Scale= 3.402823E+38
Initial Layer Thickness= 3.402823E+38
Min Layer Thickness= 3.402823E+38
Max Layer Thickness= 3.402823E+38
Number of Layers= 5

--- GUMRN.f01 (steady flow) ---

Flow Title=Flow
Program Version=6.20
Number of Profiles= 1
Profile Names=P100yr
River Rch & RM=GUMRN,Main            ,308.1
    43.7
Boundary for River Rch & Prof#=GUMRN,Main            , 1
Up Type= 0
Dn Type= 3
Dn Slope=0.028144
DSS Import GetInterval= 0
DSS Import GetPeak= 0
DSS Import FillOption= 0

--- GUMRN.g01 (geometry) ---

Geom Title=Geometry
Program Version=6.20

River Reach=GUMRN           ,Main
Reach XY= 26
     2225077.662      702941.788     2225100.707      702923.587
2225110.97405019702916.514954376     2225127.527      702908.237
2225132.02619233702906.1157034412225137.58335973702906.101561067
2225144.20092513702908.3984658422225148.25916939702907.891185308
2225151.81013313702906.1157034412225157.15928053  702902.2077624
2225161.44846326702898.5064954412225167.02854913702896.731013574
2225172.35499473702896.9846538412225180.73978533702896.867877866
 2225204.5673086702896.7310135742225223.33668833702899.774696774
     2225238.093      702905.408  2225248.700715702911.442149042
2225257.32448407702916.768594642 2225266.2018934702919.304997309
2225278.45301626702921.0639570672225306.78433607702927.928766377
2225319.46634941 702932.24065091      2225361.36      702955.885
     2225361.791      702955.321     2225442.768      703008.364

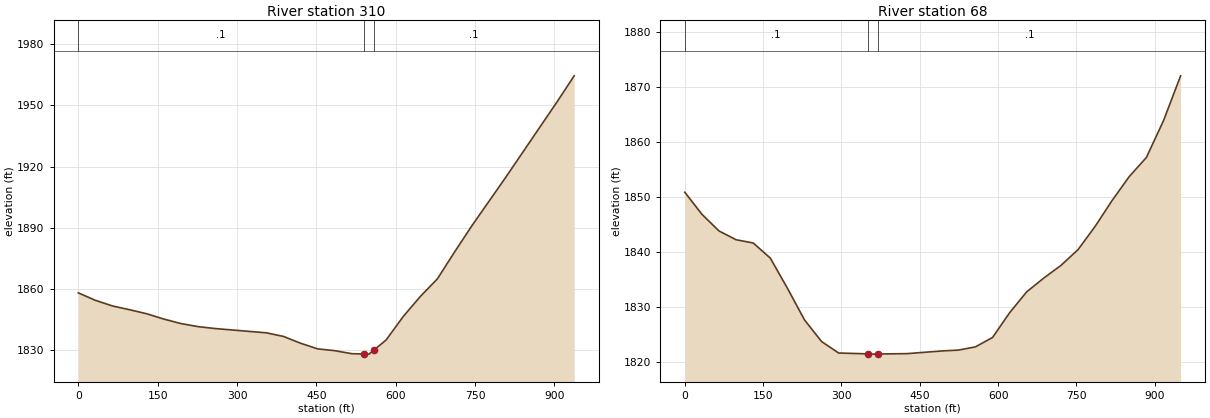
Type RM Length L Ch R = 1 ,310     ,241.2,241.2,241.2
XS GIS Cut Line= 2
     2225083.132      703464.047     2225212.761      702535.806
#Sta/Elev= 27
       0 1858.13    32.3 1854.47    64.6 1851.71      97 1849.86   129.3 1847.89
   161.6 1845.29   193.9 1843.08   226.2 1841.59   258.6 1840.64   355.5 1838.54
   387.8 1836.78   420.2 1833.43   452.5 1830.67   484.8 1829.79   517.1 1828.31
   539.4 1828.17   549.4  1828.1   559.4 1830.24   581.7 1835.01   614.1 1846.53
   646.4 1856.36   678.7 1865.01     711  1878.1   743.3 1890.81     808 1914.83
   904.9 1951.78   937.2 1964.54
#Mann= 3 ,0,0
       0      .1       0   539.4    .045       0   559.4      .1       0
Bank Sta=539.4,559.4
XS Rating Curve= 0 ,0
Exp/Cntr=0.3,0.1

Type RM Length L Ch R = 1 ,68      ,65.3,68.4,71.4
XS GIS Cut Line= 2
     2225131.743       703494.14     2225546.095      702639.973
#Sta/Elev= 29
       0 1850.79    32.7 1846.79    65.5 1843.75    98.2 1842.15     131 1841.56
   163.7 1838.82   196.4 1833.35   229.2 1827.58   261.9 1823.64   294.6 1821.55
   350.1  1821.4   360.1 1821.35   370.1 1821.37   425.6 1821.44     491 1821.92
   523.8 1822.08   556.5 1822.67   589.3 1824.38     622 1828.88   654.7 1832.68
   687.5 1835.19   720.2 1837.48   752.9 1840.34   785.7 1844.58   818.4 1849.31
   851.2 1853.66   883.9 1857.12   916.6  1863.8   949.4 1871.96
#Mann= 3 ,0,0
       0      .1       0   350.1    .045       0   370.1      .1       0
Bank Sta=350.1,370.1
XS Rating Curve= 0 ,0
Exp/Cntr=0.3,0.1
LCMann Table=0

Chan Stop Cuts=-1
Use User Specified Reach Order=0
Composite Channel Slope=5